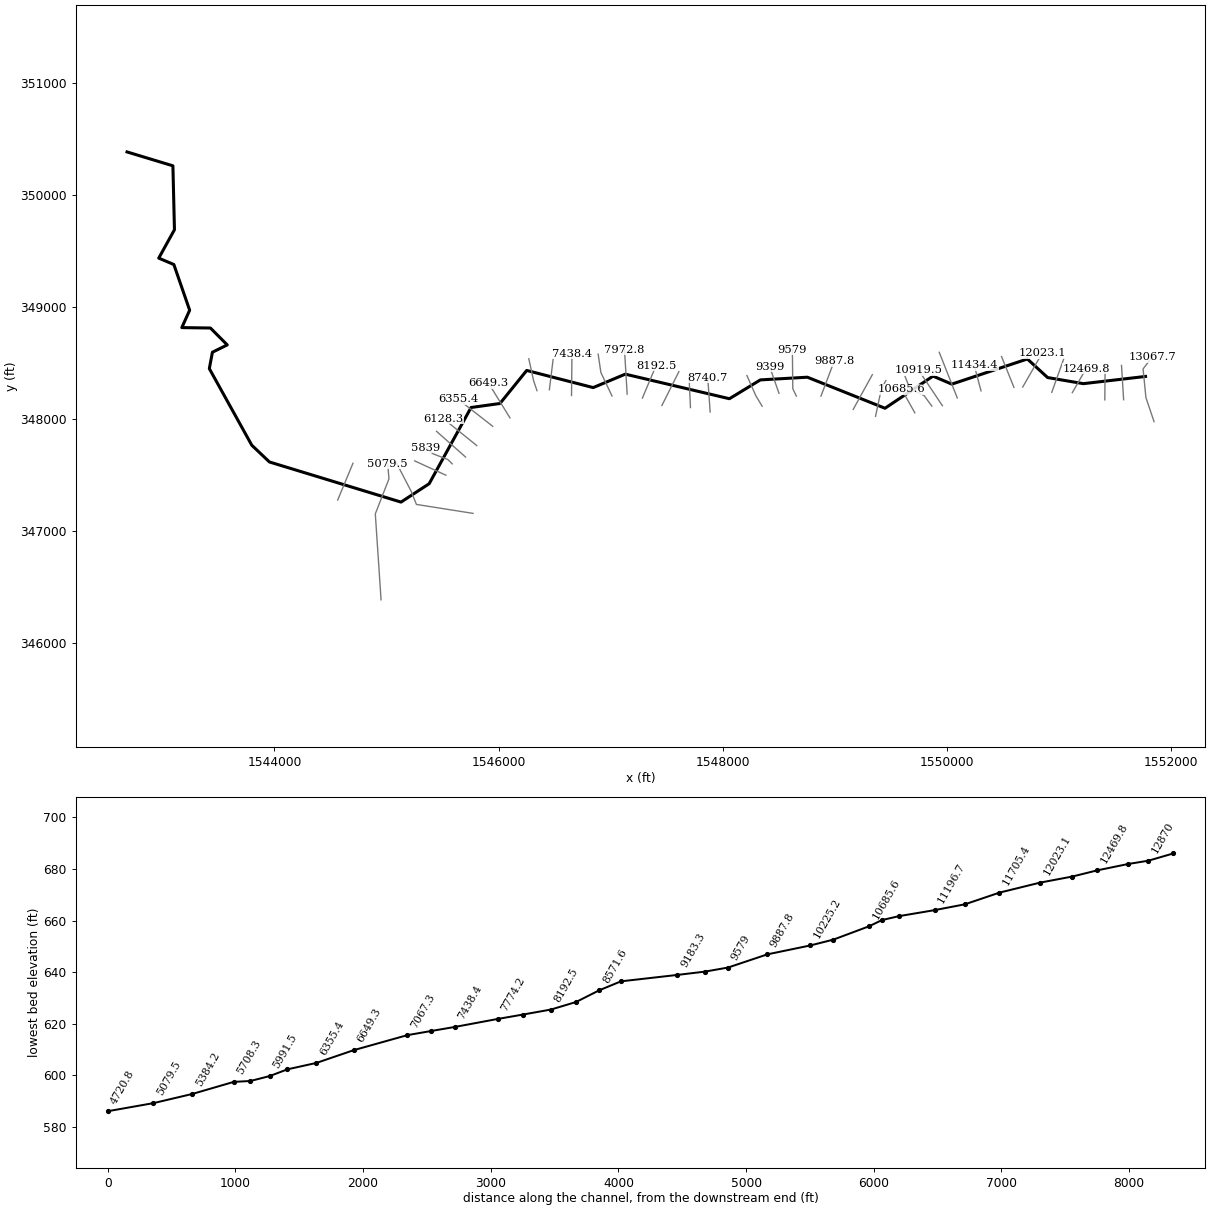
--- SOUTCMPCR.prj (project) ---

Proj Title=SOUTCMPCR
Current Plan=p01
Default Exp/Contr=0,0
English Units
Geom File=g01
Flow File=f01
Plan File=p01
BEGIN DESCRIPTION:
END DESCRIPTION:
DSS Export Rating Curves= 0
DSS Export Rating Curve Sorted= 0
DSS Export Volume Flow Curves= 0
DXF OffsetX= 0
DXF OffsetY= 0
DXF ScaleX= 0
DXF ScaleY= 0

--- SOUTCMPCR.p01 (plan) ---

Plan Title=Floodplain
Program Version=4.00
Geom File=g01
Flow File=f01
K Sum by GR=0
Std Step Tol=0.01
Critical Tol=0.01
Num of Std Step Trials=20
Max Error Tol=0.3
Flow Tol Ratio=0.001
Split Flow NTrial=30
Split Flow Tol=0.02
Split Flow Ratio=0.02
Log Output Level=0
Friction Slope Method=1
Unsteady Friction Slope Method=2
Unsteady Bridges Friction Slope Method=1
Global Log Level=0
CheckData=False
Run HTab=0
Run UNet=0
Run PostProcess=0
UNET Theta=0
UNET Theta Warmup=0
UNET ZTol=0
UNET ZSATol=0
UNET MxIter=0
UNET MaxInSteps=0
UNET DtIC=0
UNET DtMin=0
UNET MaxCRTS=0
UNET WFStab=0
UNET SFStab=0
UNET WFX=0
UNET SFX=0
UNET DSS MLevel=0
UNET DZMax Abort=0
UNET Convert EG Bridges=0
UNET Use Existing IB Tables=0
UNET Froude Limit=0
UNET Froude Power=0
Write IC File=0
Echo Input=False
Echo Output=False
Write Detailed=0

--- SOUTCMPCR.f01 (steady flow) ---

Flow Title=NFF Regression Equation
Program Version=4.00
Number of Profiles= 1
Profile Names=P100yr
River Rch & RM=SOUTCMPCR,Main            ,13067.7
362.9686
River Rch & RM=SOUTCMPCR,Main            ,12277.1
373.5043
River Rch & RM=SOUTCMPCR,Main            ,10784.6
414.7125
River Rch & RM=SOUTCMPCR,Main            ,10403.7
466.8298
River Rch & RM=SOUTCMPCR,Main            ,9887.8
471.6907
River Rch & RM=SOUTCMPCR,Main            ,9579
565.7604
River Rch & RM=SOUTCMPCR,Main            ,8389.3
579.4121
River Rch & RM=SOUTCMPCR,Main            ,5079.5
639.5903
River Rch & RM=SOUTCMPCR,Main            ,5079.5
787.7032
River Rch & RM=SOUTCMPCR,Main            ,4493.3
 795.877
Boundary for River Rch & Prof#=SOUTCMPCR,Main            , 1
Up Type= 0
Dn Type= 3
Dn Slope=0.0078
DSS Import GetInterval= 0
DSS Import GetPeak= 0
DSS Import FillOption= 0

--- SOUTCMPCR.g01 (geometry) ---

Geom Title=Geometry
Program Version=4.00

River Reach=SOUTCMPCR       ,Main
Reach XY= 30
     1551774.725      348377.648     1551219.743      348313.232
     1550900.604      348367.729     1550719.922      348533.435
     1550045.442      348309.007     1549877.746       348380.62
     1549449.268      348093.745      1548756.15      348370.803
     1548336.675      348346.748     1548060.402      348178.749
     1547131.194      348398.087     1546844.553      348278.127
     1546251.123      348431.088     1546012.522      348136.201
     1545754.519      348100.415      1545380.63      347420.188
     1545129.289      347256.098     1543955.271      347614.041
     1543797.287      347763.744     1543418.352       348447.49
     1543445.865      348593.696     1543578.305      348659.111
     1543428.129      348809.852     1543172.835      348813.487
     1543242.748      348968.908     1543101.696      349376.711
     1542966.807      349433.621     1543107.072      349687.067
     1543093.289      350257.558     1542683.688      350381.605

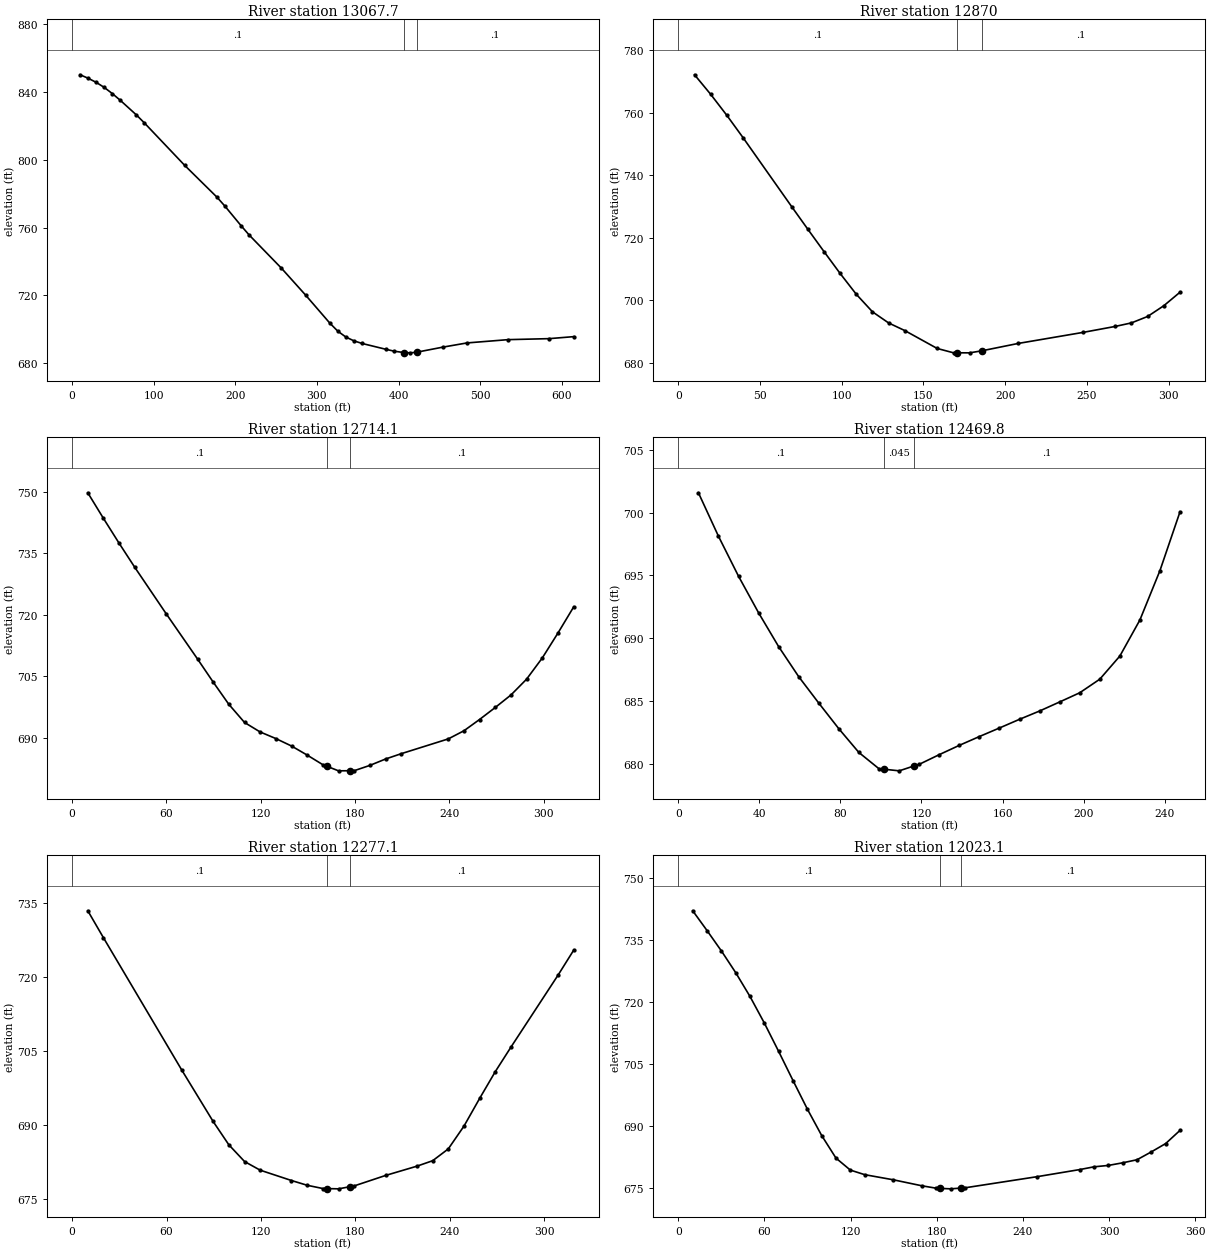
Type RM Length L Ch R = 1 ,13067.7 ,198.5,197.8,197
XS GIS Cut Line= 4
     1551850.791      347973.941     1551778.138      348188.741
     1551752.867      348444.606     1551831.838      348548.847
#Sta/Elev= 30
     9.9  850.17    19.7  848.12    29.6  845.69    39.4  842.71    49.3  839.08
    59.2  835.05    78.9  826.43    88.7   821.7     138  796.69   177.5  777.93
   187.3  772.62     207  761.13   216.9  755.63   256.4  736.06   286.1  720.13
   315.8  703.57   325.6  698.81   335.5  695.34   345.4   693.1   355.3  691.57
     385  688.06   394.9  686.98   407.1  686.17   414.6  686.03   422.1  686.39
   454.2  689.39   483.9  691.88   534.2  693.82   584.5  694.41   614.6  695.59
#Mann= 3 , 0 , 0
       0      .1       0   407.1    .045       0   422.1      .1       0
Bank Sta=407.1,422.1
XS Rating Curve= 0 ,0
Exp/Cntr=0.3,0.1

Type RM Length L Ch R = 1 ,12870   ,157.6,155.9,154.3
XS GIS Cut Line= 2
     1551579.132      348169.788     1551560.179      348476.194
#Sta/Elev= 24
     9.9  772.21    19.8  765.94    29.7   759.2    39.6  752.07    69.3  730.03
    79.2  722.78    89.1  715.63      99   708.6   108.9  701.93   118.8  696.32
   128.7  692.75   138.6  690.31   158.4  684.59   168.4   683.2   170.8   683.2
   178.3  683.19   185.8  683.85     208   686.2   247.6  689.73   267.4  691.65
   277.3  692.78   287.2  694.84   297.1  698.28     307   702.6
#Mann= 3 , 0 , 0
       0      .1       0   170.8    .045       0   185.8      .1       0
Bank Sta=170.8,185.8
XS Rating Curve= 0 ,0
Exp/Cntr=0.3,0.1

Type RM Length L Ch R = 1 ,12714.1 ,256,244.3,232.5
XS GIS Cut Line= 2
     1551411.157      348168.553     1551414.316      348487.594
#Sta/Elev= 30
      10   749.7    19.9   743.5    29.9  737.42    39.9  731.53    59.8  720.26
    79.8   709.2    89.7  703.61    99.7  698.16   109.7  693.73   119.6  691.42
   129.6  689.81   139.6  687.99   149.6  685.77   159.5  683.44     162  683.07
   169.5  681.94     177  681.97   179.5  681.98   189.4  683.26   199.4  684.82
   209.4  686.12   239.3  689.72   249.3  691.71   259.2  694.45   269.2  697.38
   279.2  700.43   289.1  704.27   299.1  709.44   309.1  715.53   319.1   721.9
#Mann= 3 , 0 , 0
       0      .1       0     162    .045       0     177      .1       0
Bank Sta=162,177
XS Rating Curve= 0 ,0
Exp/Cntr=0.3,0.1

Type RM Length L Ch R = 1 ,12469.8 ,189.1,192.7,196.8
XS GIS Cut Line= 2
     1551121.103      348232.965     1551244.297      348447.765
#Sta/Elev= 27
     9.9  701.57    19.8  698.11    29.7  694.93    39.6  692.02    49.5  689.33
    59.4  686.94    69.3  684.84    79.2   682.8    89.1  680.91      99  679.62
   101.5  679.58     109  679.45   116.5  679.85   118.9  679.97   128.8  680.74
   138.7  681.48   148.6  682.18   158.5  682.86   168.4  683.55   178.3  684.21
   188.2  684.93   198.1  685.66     208  686.74   217.9  688.58   227.8  691.45
   237.7  695.38   247.6  700.06
#Mann= 3 , 0 , 0
       0      .1       0   101.5    .045       0   116.5      .1       0
Bank Sta=101.5,116.5
XS Rating Curve= 0 ,0
Exp/Cntr=0.3,0.1

Type RM Length L Ch R = 1 ,12277.1 ,256.8,254,251.8
XS GIS Cut Line= 2
     1550937.891      348236.124     1551045.291      348536.212
#Sta/Elev= 24
      10  733.52    19.9  728.07    69.7  701.19    89.6  690.77    99.6  686.02
   109.6  682.62   119.5  680.87   139.4  678.77   149.4   677.8   159.4  677.14
   161.8  677.13   169.3  677.08   176.8  677.53   179.3  677.68   199.2   679.8
   219.1  681.68   229.1  682.79     239  685.18     249  689.82     259  695.47
   268.9  700.88   278.9  705.88   308.8  720.48   318.7  725.53
#Mann= 3 , 0 , 0
       0      .1       0   161.8    .045       0   176.8      .1       0
Bank Sta=161.8,176.8
XS Rating Curve= 0 ,0
Exp/Cntr=0.3,0.1

Type RM Length L Ch R = 1 ,12023.1 ,292.5,317.7,337.5
XS GIS Cut Line= 2
     1550678.868      348283.506     1550852.603      348586.753
#Sta/Elev= 29
      10  742.15      20  737.34      30   732.4    39.9  727.17    49.9  721.37
    59.9  714.92    69.9  708.02    79.9  700.96    89.9  694.03    99.9  687.61
   109.8  682.17   119.8  679.26   129.8  678.15   149.8   676.9   169.8  675.44
   179.7  674.86   182.2  674.82   189.7  674.71   197.2   674.9   199.7  674.96
   249.6  677.64   279.6  679.38   289.6  680.05   299.6  680.39   309.5  681.02
   319.5  681.76   329.5  683.67   339.5  685.69   349.5  688.89
#Mann= 3 , 0 , 0
       0      .1       0   182.2    .045       0   197.2      .1       0
Bank Sta=182.2,197.2
XS Rating Curve= 0 ,0
Exp/Cntr=0.3,0.1

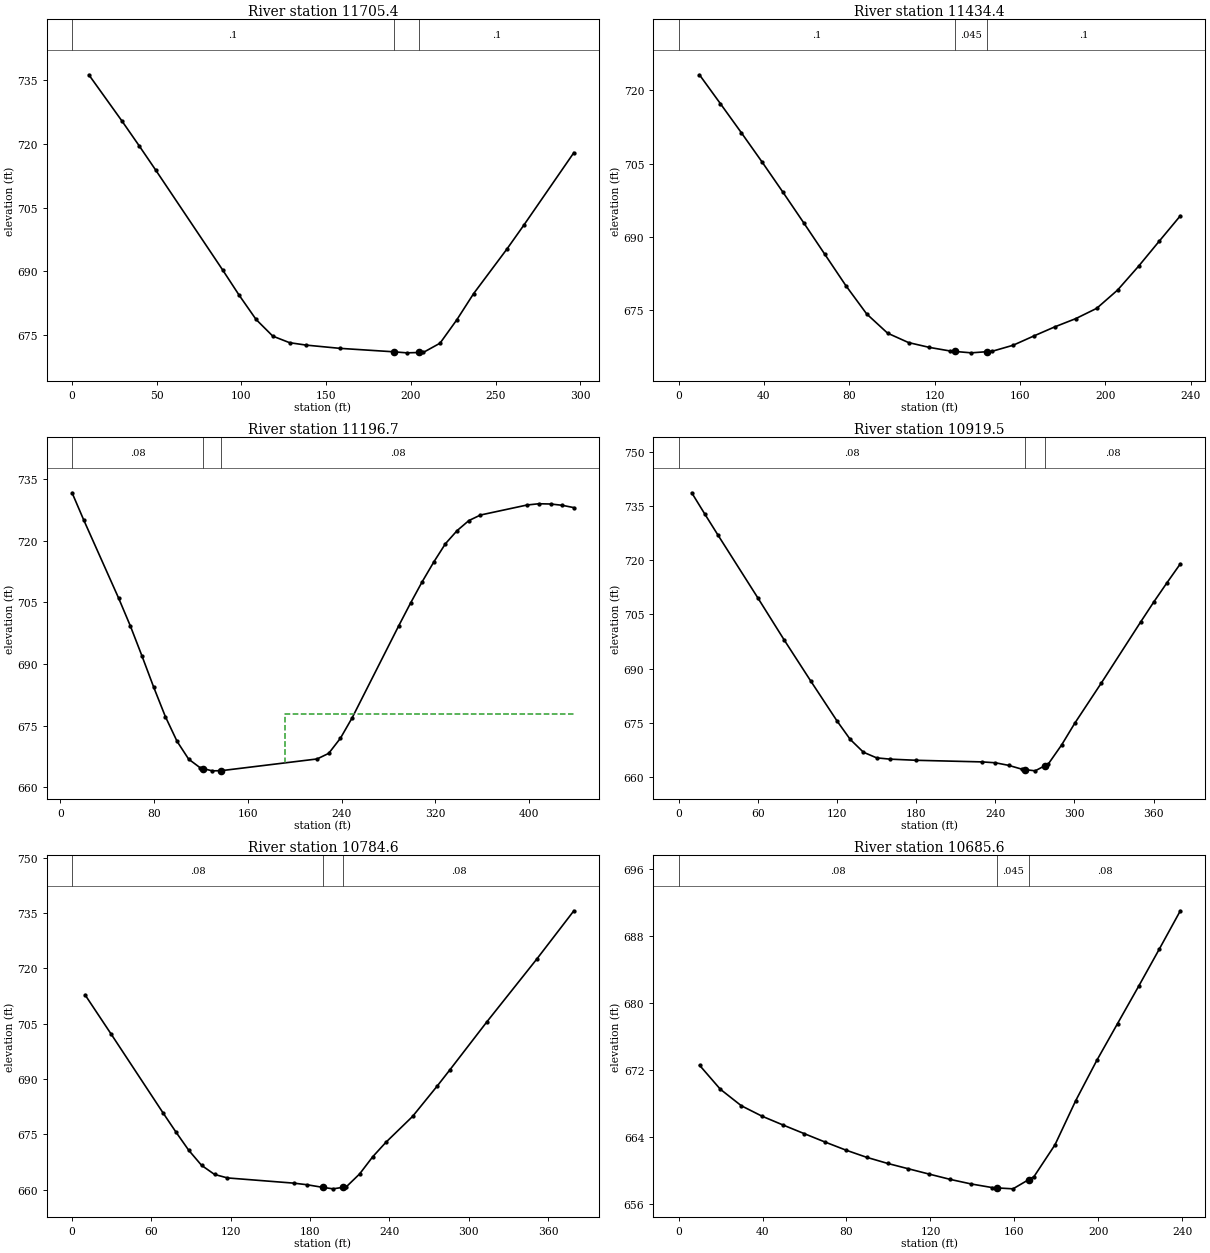
Type RM Length L Ch R = 1 ,11705.4 ,273.8,271,268.2
XS GIS Cut Line= 2
     1550599.897      348280.347     1550489.338      348555.165
#Sta/Elev= 21
     9.9  736.32    29.6  725.35    39.5  719.66    49.4  713.86    88.9  690.35
    98.7  684.37   108.6  678.71   118.5  674.77   128.4  673.23   138.2  672.66
     158   671.9     190  671.08   197.5  670.84     205  670.92   207.4  670.95
   217.2  673.11   227.1  678.61     237  684.77   256.7  695.29   266.6  700.87
   296.2  717.98
#Mann= 3 , 0 , 0
       0      .1       0     190    .045       0     205      .1       0
Bank Sta=190,205
XS Rating Curve= 0 ,0
Exp/Cntr=0.3,0.1

Type RM Length L Ch R = 1 ,11434.4 ,235,237.7,240.5
XS GIS Cut Line= 2
     1550306.127      348248.759     1550246.109      348476.194
#Sta/Elev= 26
     9.8  723.17    19.6  717.28    29.4  711.35    39.2  705.31      49  699.12
    58.8  692.82    68.6  686.44    78.4  680.07    88.2  674.26      98  670.33
   107.8  668.41   117.6  667.42   127.4  666.68   129.7  666.59   137.2  666.31
   144.7  666.55     147  666.63   156.8  667.86   166.6  669.77   176.4  671.63
   186.2  673.31     196  675.41   205.8  679.15   215.6  684.01   225.4  689.19
   235.2  694.33
#Mann= 3 , 0 , 0
       0      .1       0   129.7    .045       0   144.7      .1       0
Bank Sta=129.7,144.7
XS Rating Curve= 0 ,0
Exp/Cntr=0.3,0.1

Type RM Length L Ch R = 1 ,11196.7 ,272.5,277.2,281.8
XS GIS Cut Line= 2
     1550094.486      348185.583     1549933.386      348593.071
#Sta/Elev= 30
      10  731.67    19.9  725.08    49.8     706    59.8  699.24    69.7  691.95
    79.7  684.36    89.6  677.25    99.6  671.22   109.5  666.89   119.5  664.76
     122  664.59   129.5  664.05     137  664.08   219.1  666.94     229   668.3
     239  671.98     249  676.94   288.8  699.35   298.8  704.82   308.7     710
   318.7  714.85   328.6  719.28   338.6  722.48   348.6  724.91   358.5  726.26
   398.3   728.7   408.3     729   418.3  728.94   428.2  728.63   438.2  728.06
#Mann= 3 , 0 , 0
      10     .08       0     122    .045       0     137     .08       0
#XS Ineff= 2 , 0
                          191.31          677.83
Permanent Ineff=
       F       F
Bank Sta=122,137
XS Rating Curve= 0 ,0
Exp/Cntr=0.3,0.1

Type RM Length L Ch R = 1 ,10919.5 ,122.7,134.8,147
XS GIS Cut Line= 2
     1549961.815      348116.088     1549750.174      348431.971
#Sta/Elev= 27
      10  738.67      20  732.73      30   726.9      60  709.64      80  697.98
   100.1  686.63   120.1  675.53   130.1  670.43   140.1  666.89   150.1  665.33
   160.1  664.98   180.1  664.66   230.1  664.21   240.1  663.97   250.2  663.25
   260.2  662.19   262.7  662.08   270.2  661.74   277.7  663.18   280.2  663.66
   290.2  668.87   300.2   674.9   320.2  685.96   350.2  702.96   360.2  708.52
   370.2  713.84   380.2  719.01
#Mann= 3 , 0 , 0
       0     .08       0   262.7    .045       0   277.7     .08       0
Bank Sta=262.7,277.7
XS Rating Curve= 0 ,0
Exp/Cntr=0.3,0.1

Type RM Length L Ch R = 1 ,10784.6 ,113,99,85
XS GIS Cut Line= 4
      1549867.05       348112.93     1549797.556      348207.694
     1549671.203      348267.712      1549626.98       348381.43
#Sta/Elev= 23
     9.8  712.85    29.4  702.27    68.6  680.91    78.3  675.74    88.1  670.72
    97.9  666.58   107.7  664.11   117.5  663.16   167.5  661.75   177.5  661.32
   189.9  660.58   197.4   660.2   204.9  660.62   207.4  660.77   217.4  664.24
   227.4  668.94   237.4  672.87   257.4  679.83   276.2  688.15   285.6  692.46
   313.7  705.55   351.3  722.52   379.4  735.65
#Mann= 3 , 0 , 0
       0     .08       0   189.9    .045       0   204.9     .08       0
Bank Sta=189.9,204.9
XS Rating Curve= 0 ,0
Exp/Cntr=0.3,0.1

Type RM Length L Ch R = 1 ,10685.6 ,298.1,281.9,265.6
XS GIS Cut Line= 2
     1549715.427      348052.912      1549598.55      348261.394
#Sta/Elev= 26
      10  672.57    19.9  669.71    29.9  667.74    39.8  666.49    49.8  665.44
    59.8  664.42    69.7  663.42    79.7  662.45    89.6  661.59    99.6  660.86
   109.5  660.22   119.5  659.58   129.5  658.95   139.4  658.41   149.4  657.98
   151.8  657.94   159.3  657.83   166.8  658.93   169.3  659.29   179.3  663.08
   189.2  668.36   199.2  673.14   209.1  677.54   219.1  681.97     229  686.43
     239  690.99
#Mann= 3 , 0 , 0
       0     .08       0   151.8    .045       0   166.8     .08       0
Bank Sta=151.8,166.8
XS Rating Curve= 0 ,0
Exp/Cntr=0.3,0.1

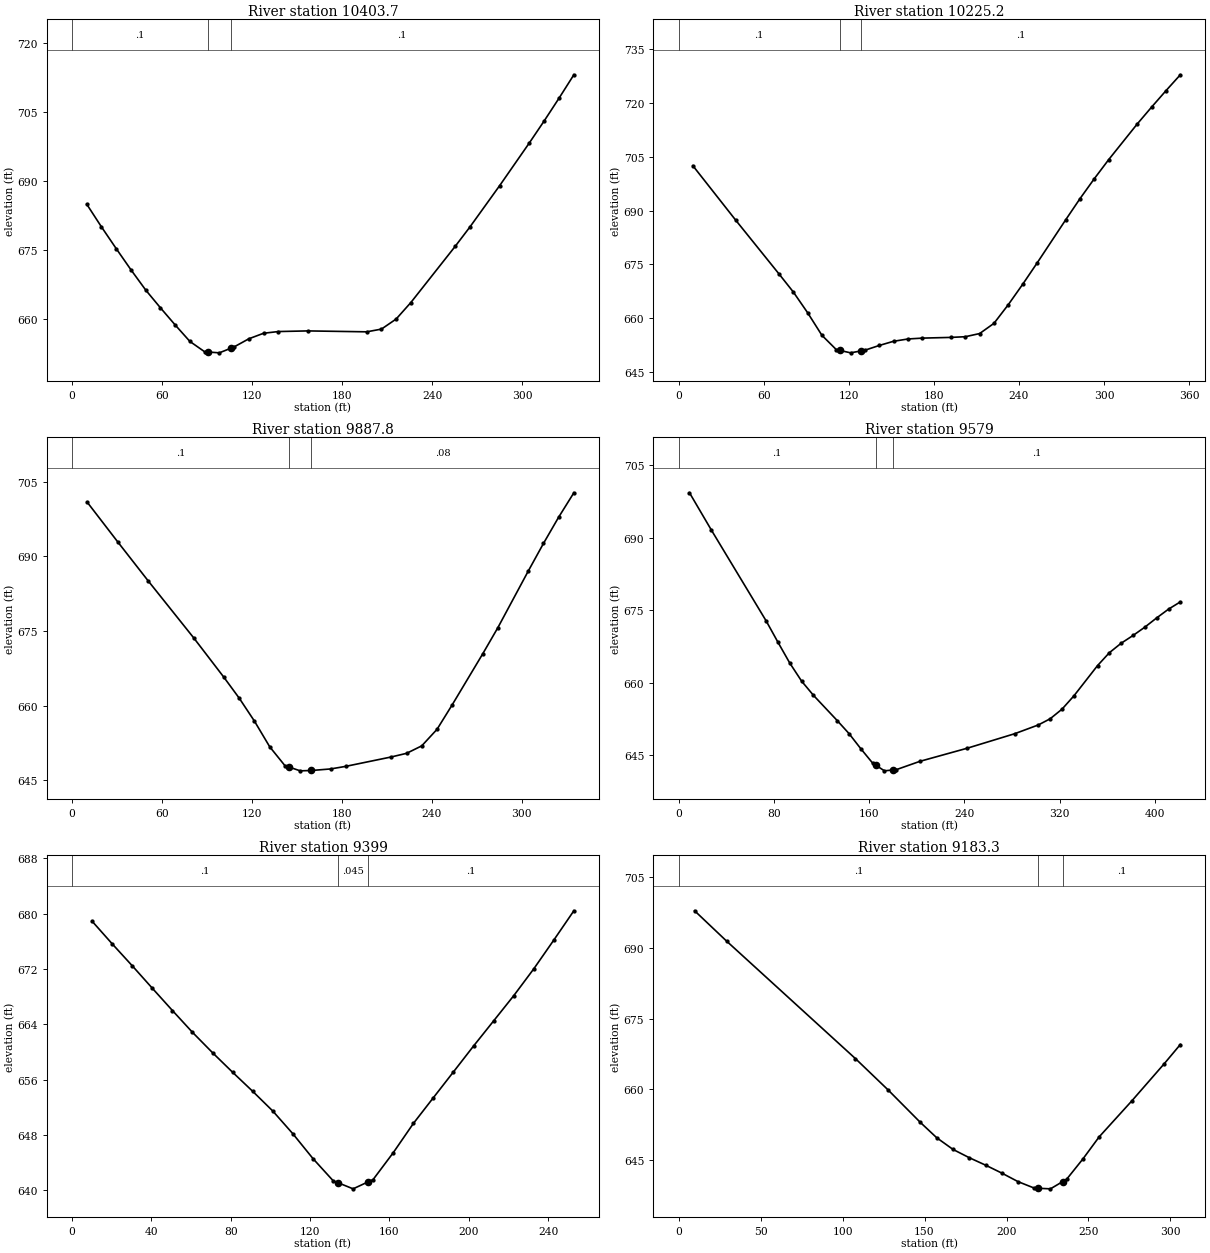
Type RM Length L Ch R = 1 ,10403.7 ,185.3,178.6,171.9
XS GIS Cut Line= 3
     1549364.798      348021.324     1549415.339      348261.394
     1549456.403      348340.365
#Sta/Elev= 28
     9.8  684.93    19.6     680    29.4  675.29    39.3  670.65    49.1  666.26
    58.9   662.4    68.7  658.68    78.5   655.1    88.3  652.86    90.6   652.8
    98.1  652.62   105.6   653.6   107.9   653.9   117.8  655.68   127.6  656.88
   137.4  657.25     157  657.39   196.3  657.19   206.1  657.78   215.9  659.97
   225.7  663.56   255.2  675.76   265.1  680.01   284.9     689   304.7   698.3
   314.6  703.09   324.5  708.04   334.3  713.09
#Mann= 3 , 0 , 0
       0      .1       0    90.6    .045       0   105.6      .1       0
Bank Sta=90.6,105.6
XS Rating Curve= 0 ,0
Exp/Cntr=0.3,0.1

Type RM Length L Ch R = 1 ,10225.2 ,334.1,337.3,340.6
XS GIS Cut Line= 2
     1549165.478        348083.5     1549336.245       348393.41
#Sta/Elev= 30
    10.1   702.5    40.4  687.29    70.8  672.38    80.9  667.35      91  661.57
   101.1  655.27   111.2   651.3   113.8  651.06   121.3  650.39   128.8  650.93
   131.4  651.12   141.5  652.44   151.6  653.61   161.8  654.25   171.9  654.49
   192.1  654.69   202.2  654.88   212.3  655.76   222.4   658.6   232.5   663.8
   242.6  669.45   252.7  675.34     273  687.45   283.1  693.35   293.2  698.91
   303.3   704.2   323.5  714.16   333.6  718.85   343.7   723.4   353.8  727.82
#Mann= 3 , 0 , 0
       0      .1       0   113.8    .045       0   128.8      .1       0
Bank Sta=113.8,128.8
XS Rating Curve= 0 ,0
Exp/Cntr=0.3,0.1

Type RM Length L Ch R = 1 ,9887.8  ,300.4,308.8,317.3
XS GIS Cut Line= 2
     1548877.704      348202.088     1548996.292      348515.161
#Sta/Elev= 25
    10.1  700.91    30.4  692.96    50.7  685.13    81.2  673.63   101.4  665.69
   111.6   661.5   121.7  656.91   131.9  651.75     142  647.98   144.7   647.7
   152.2  646.93   159.7     647   172.5  647.31   182.6  647.83     213  649.72
   223.2  650.45   233.3  651.95   243.5  655.27   253.6  660.18   273.9  670.39
   284.1   675.7   304.3  687.03   314.5  692.61   324.6  697.87   334.8   702.8
#Mann= 3 , 0 , 0
       0      .1       0   144.7    .045       0   159.7     .08       0
Bank Sta=144.7,159.7
XS Rating Curve= 0 ,0
Exp/Cntr=0.3,0.1

Type RM Length L Ch R = 1 ,9579    ,172.7,180,187.3
XS GIS Cut Line= 3
      1548657.92      348202.088     1548626.297      348268.497
     1548622.355      348616.234
#Sta/Elev= 30
     9.2  699.35    27.6  691.62    73.6  672.82    83.5  668.41    93.4  664.11
   103.4  660.35   113.3  657.43   133.2  652.22   143.1  649.53     153   646.4
     163   643.4   165.4  643.01   172.9  641.81   180.4     642   182.9  642.06
   202.7  643.78   242.5   646.5   282.2  649.49   302.1  651.31     312  652.58
     322  654.58   331.9  657.31   351.8  663.59   361.7  666.25   371.6  668.21
   381.6  669.82   391.5  671.54   401.4  673.45   411.4  675.27   421.3  676.77
#Mann= 3 , 0 , 0
       0      .1       0   165.4    .045       0   180.4      .1       0
Bank Sta=165.4,180.4
XS Rating Curve= 0 ,0
Exp/Cntr=0.3,0.1

Type RM Length L Ch R = 1 ,9399    ,213.8,215.7,217.5
XS GIS Cut Line= 2
     1548502.965      348227.387     1548419.163      348466.144
#Sta/Elev= 27
    10.1  678.93    20.2  675.67    30.4  672.47    40.5  669.23    50.6  666.02
    60.7  662.87    70.9   659.9      81  657.08    91.1  654.33   101.2  651.49
   111.3  648.21   121.5   644.6   131.6  641.42   134.2  641.11   141.7  640.24
   149.2  641.24   151.8  641.59   161.9  645.45   172.1   649.7   182.2  653.43
   192.3  657.15   202.4  660.88   212.6  664.54   222.7  668.17   232.8  672.05
   242.9  676.21     253  680.44
#Mann= 3 , 0 , 0
       0      .1       0   134.2    .045       0   149.2      .1       0
Bank Sta=134.2,149.2
XS Rating Curve= 0 ,0
Exp/Cntr=0.3,0.1

Type RM Length L Ch R = 1 ,9183.3  ,450.7,442.6,434.5
XS GIS Cut Line= 3
     1548352.753      348111.961     1548296.975      348204.357
     1548216.772      348385.504
#Sta/Elev= 21
     9.8  697.82    29.4  691.37   107.9  666.52   127.7  659.93   147.5  653.01
   157.5  649.76   167.4   647.3   177.3  645.55   187.2  643.98   197.1   642.3
     207  640.49   216.9  639.12   219.3  639.08   226.8  638.96   234.3   640.5
   236.7     641   246.6  645.29   256.5  649.96   276.3  657.53   296.1  665.41
     306  669.51
#Mann= 3 , 0 , 0
       0      .1       0   219.3    .045       0   234.3      .1       0
Bank Sta=219.3,234.3
XS Rating Curve= 0 ,0
Exp/Cntr=0.3,0.1

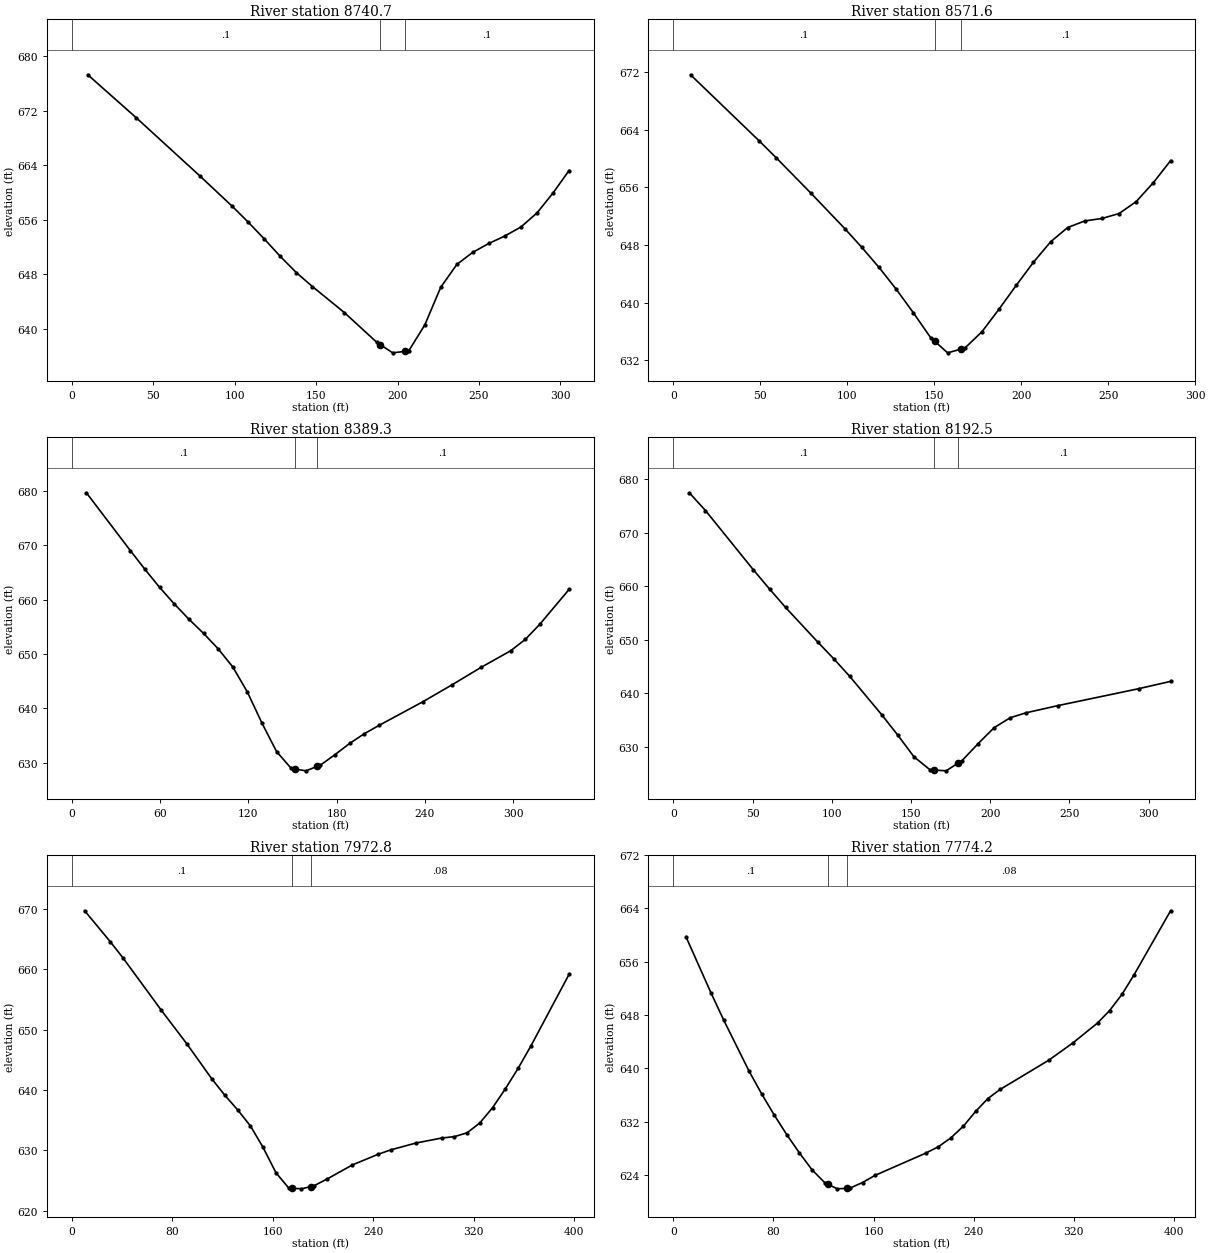
Type RM Length L Ch R = 1 ,8740.7  ,169.7,169.1,168.6
XS GIS Cut Line= 2
     1547888.566        348060.4     1547867.332      348364.949
#Sta/Elev= 25
     9.8  677.31    39.4  671.03    78.8  662.41    98.5  657.99   108.3  655.66
   118.2  653.19     128  650.63   137.9  648.24   147.7  646.21   167.4  642.37
   187.1  638.04   189.5  637.66     197  636.47   204.5  636.68   206.8  636.74
   216.7  640.57   226.5   646.1   236.4  649.46   246.2  651.24     256  652.53
   265.9  653.64   275.7  654.95   285.6  657.02   295.4  659.94   305.3  663.25
#Mann= 3 , 0 , 0
       0      .1       0   189.5    .045       0   204.5      .1       0
Bank Sta=189.5,204.5
XS Rating Curve= 0 ,0
Exp/Cntr=0.3,0.1

Type RM Length L Ch R = 1 ,8571.6  ,193.9,182.3,170.6
XS GIS Cut Line= 2
     1547712.808      348099.946     1547699.728      348385.504
#Sta/Elev= 26
     9.9  671.66    49.3  662.49    59.1  660.14    78.9  655.26    98.6  650.28
   108.4  647.67   118.3  644.88   128.1  641.88     138  638.59   147.9  635.15
   150.2  634.65   157.7  633.02   165.2  633.52   167.6  633.68   177.4  635.94
   187.3   639.1   197.1  642.38     207  645.59   216.9  648.44   226.7  650.43
   236.6  651.35   246.4  651.69   256.3  652.38   266.1  654.03     276  656.67
   285.9  659.73
#Mann= 3 , 0 , 0
       0      .1       0   150.2    .045       0   165.2      .1       0
Bank Sta=150.2,165.2
XS Rating Curve= 0 ,0
Exp/Cntr=0.3,0.1

Type RM Length L Ch R = 1 ,8389.3  ,195.3,196.8,198.4
XS GIS Cut Line= 2
     1547457.808      348118.286       1547609.6       348420.29
#Sta/Elev= 28
     9.9   679.7    39.8  669.04    49.7  665.59    59.6  662.29    69.6  659.23
    79.5  656.43    89.5   653.8    99.4  650.97   109.4  647.61   119.3     643
   129.2  637.28   139.2     632   149.1  628.93   151.6  628.81   159.1  628.47
   166.6  629.27     169  629.53   178.9  631.46   188.9  633.53   198.8  635.31
   208.8  636.84   238.6   641.2   258.5  644.33   278.4  647.57   298.2  650.58
   308.2  652.68   318.1  655.48     338   661.9
#Mann= 3 , 0 , 0
       0      .1       0   151.6    .045       0   166.6      .1       0
Bank Sta=151.6,166.6
XS Rating Curve= 0 ,0
Exp/Cntr=0.3,0.1

Type RM Length L Ch R = 1 ,8192.5  ,209.2,219.6,230
XS GIS Cut Line= 2
     1547283.878      348184.695     1547405.629       348474.05
#Sta/Elev= 23
    10.1  677.41    20.3   674.1    50.6  663.01    60.8  659.44    70.9  656.01
    91.1  649.59   101.3  646.44   111.4  643.15   131.6  635.99   141.8  632.16
   151.9  628.16     162  625.75   164.7  625.69   172.2  625.54   179.7  626.97
   182.3  627.46   192.4  630.61   202.5  633.59   212.7  635.45   222.8  636.38
     243  637.72   293.7  640.86   313.9  642.23
#Mann= 3 , 0 , 0
       0      .1       0   164.7    .045       0   179.7      .1       0
Bank Sta=164.7,179.7
XS Rating Curve= 0 ,0
Exp/Cntr=0.3,0.1

Type RM Length L Ch R = 1 ,7972.8  ,190,198.6,207.2
XS GIS Cut Line= 2
     1547147.897      348219.481      1547124.18      348614.775
#Sta/Elev= 30
    10.2  669.68    30.5  664.58    40.6  661.91    71.1  653.24    91.4  647.68
   111.7  641.76   121.8  639.12     132   636.7   142.2  634.03   152.3  630.46
   162.5  626.29   172.6  623.76   175.3  623.71   182.8   623.6   190.3  623.98
   192.9  624.11   203.1  625.21   223.4  627.56   243.7  629.31   253.8  630.05
   274.2   631.2   294.5  632.02   304.6  632.25   314.8  632.89   324.9  634.52
   335.1  637.06   345.2  640.16   355.4  643.57   365.5  647.25     396  659.16
#Mann= 3 , 0 , 0
       0      .1       0   175.3    .045       0   190.3     .08       0
Bank Sta=175.3,190.3
XS Rating Curve= 0 ,0
Exp/Cntr=0.3,0.1

Type RM Length L Ch R = 1 ,7774.2  ,345.5,335.8,326
XS GIS Cut Line= 3
     1547012.416      348203.403     1546913.093       348412.95
     1546888.942      348576.689
#Sta/Elev= 30
    10.1  659.75    30.2  651.28    40.3  647.22    60.5  639.58    70.6  636.15
    80.7  632.96    90.7  630.02   100.8  627.28   110.9  624.74     121  622.82
   123.6  622.58   131.1  621.89   138.6  621.97   141.2     622   151.2  622.84
   161.3  623.92   201.6  627.24   211.7   628.2   221.8  629.54   231.9  631.32
   241.6  633.52   251.4  635.45   261.1  636.81     300   641.2   319.5  643.83
     339  646.79   348.7  648.67   358.5  651.08   368.2  654.03   397.4  663.65
#Mann= 3 , 0 , 0
       0      .1       0   123.6    .045       0   138.6     .08       0
Bank Sta=123.6,138.6
XS Rating Curve= 0 ,0
Exp/Cntr=0.3,0.1

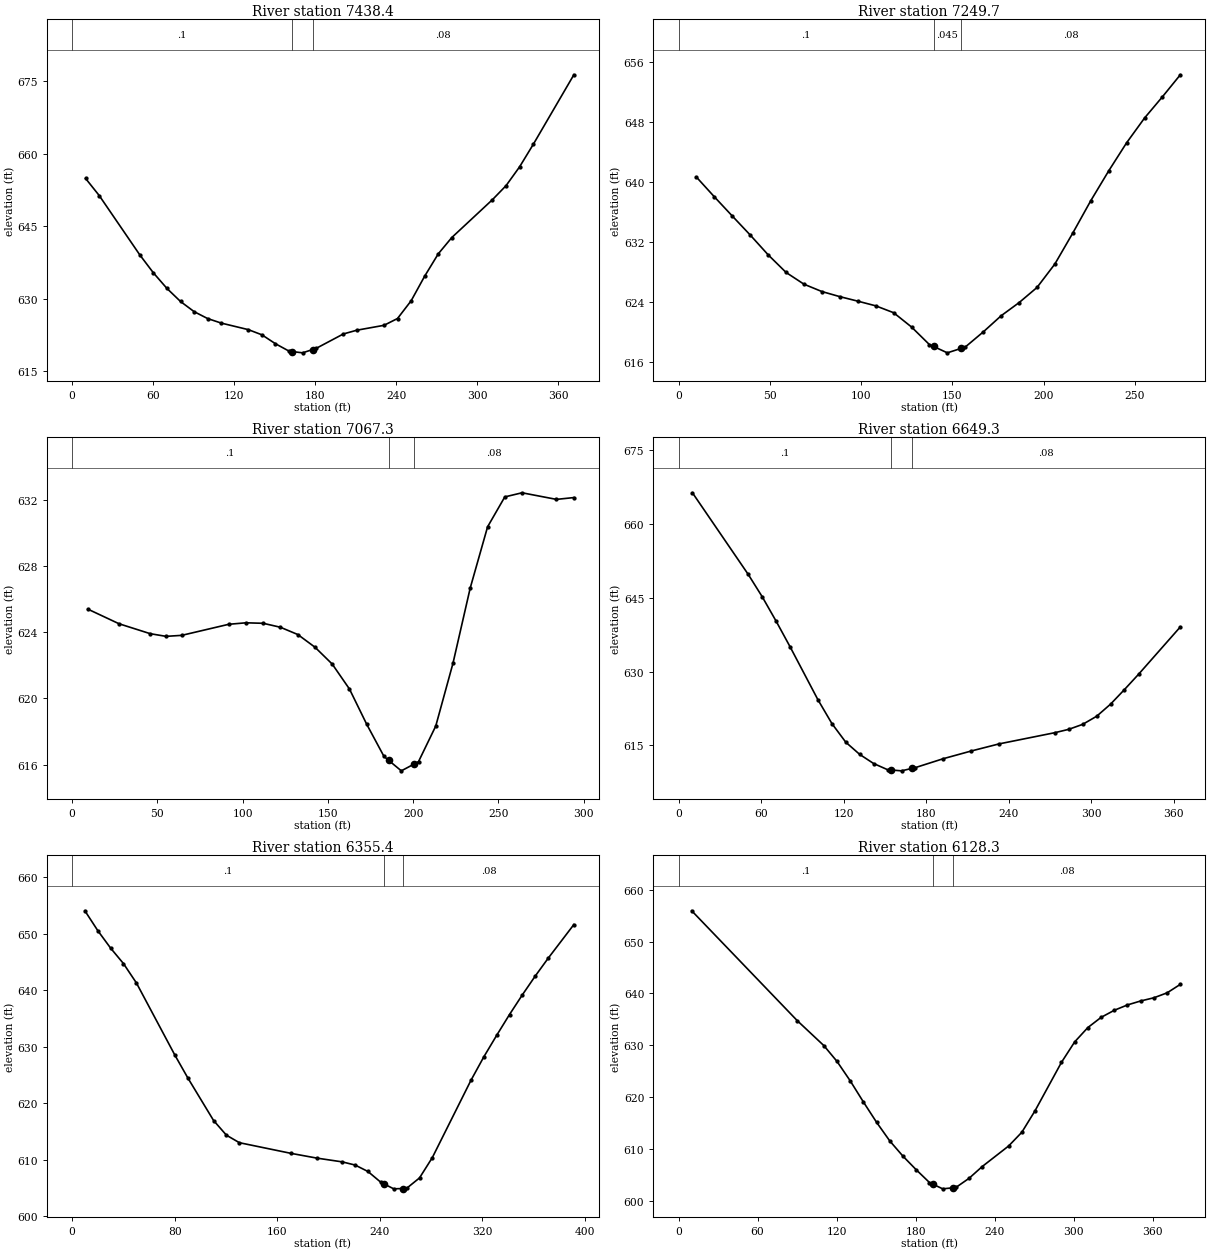
Type RM Length L Ch R = 1 ,7438.4  ,191.7,188.7,185.7
XS GIS Cut Line= 2
      1546651.21      348207.424     1546655.163      348579.001
#Sta/Elev= 30
      10  654.91    20.1  651.37    50.2  639.06    60.3  635.33    70.3  632.12
    80.3  629.43    90.4  627.32   100.4  625.89   110.5  624.95   130.6  623.59
   140.6  622.52   150.6  620.68   160.7  619.14   163.2  619.05   170.7  618.79
   178.2  619.48   180.8  619.72   200.9   622.7   210.9  623.48     231  624.49
     241   625.9   251.1  629.57   261.1  634.66   271.2   639.3   281.2  642.67
   311.3  650.51   321.4  653.42   331.4  657.31   341.5  661.95   371.6  676.38
#Mann= 3 , 0 , 0
       0      .1       0   163.2    .045       0   178.2     .08       0
Bank Sta=163.2,178.2
XS Rating Curve= 0 ,0
Exp/Cntr=0.3,0.1

Type RM Length L Ch R = 1 ,7249.7  ,174.6,182.5,190.4
XS GIS Cut Line= 2
     1546453.563      348258.812     1546487.163      348531.565
#Sta/Elev= 30
     9.8  640.67    19.6  638.04    29.4  635.48    39.3  632.92    49.1  630.28
    58.9  627.93    68.7  626.36    78.5  625.38    88.3   624.7    98.1   624.1
     108  623.47   117.8  622.55   127.6  620.64   137.4  618.29   139.7  618.04
   147.2  617.19   154.7  617.78     157  617.96   166.9  619.99   176.7  622.15
   186.5   623.9   196.3  625.92   206.1  629.06   215.9  633.19   225.7  637.49
   235.6  641.51   245.4  645.26   255.2  648.56     265   651.4   274.8  654.34
#Mann= 3 , 0 , 0
       0      .1       0   139.7    .045       0   154.7     .08       0
Bank Sta=139.7,154.7
XS Rating Curve= 0 ,0
Exp/Cntr=0.3,0.1

Type RM Length L Ch R = 1 ,7067.3  ,410.5,417.9,425.3
XS GIS Cut Line= 3
     1546342.881      348250.907     1546313.234      348337.871
     1546269.752      348535.518
#Sta/Elev= 27
     9.2  625.41    27.6  624.52    45.9  623.92    55.1  623.76    64.3  623.82
    91.9  624.49     102  624.58   112.1  624.55   122.2  624.31   132.4  623.87
   142.5   623.1   152.6  622.08   162.7  620.57   172.8  618.44   182.9   616.5
   185.6  616.26   193.1  615.62   200.6  616.03   203.2  616.18   213.3  618.33
   223.4  622.13   233.5  626.68   243.7  630.39   253.8   632.2   263.9  632.45
   284.1  632.05   294.3  632.16
#Mann= 3 , 0 , 0
       0      .1       0   185.6    .045       0   200.6     .08       0
Bank Sta=185.6,200.6
XS Rating Curve= 0 ,0
Exp/Cntr=0.3,0.1

Type RM Length L Ch R = 1 ,6649.3  ,285.9,293.9,302
XS GIS Cut Line= 2
     1546101.752      348007.801     1545910.034      348318.107
#Sta/Elev= 26
    10.1   666.3    50.7  649.71    60.8   645.2    70.9  640.25    81.1  635.02
   101.3  624.29   111.5  619.43   121.6  615.64   131.7  613.17   141.8  611.32
     152  610.06   154.6     610   162.1  609.83   169.6  610.32   172.2  610.49
   192.5   612.3   212.8  613.86     233   615.3   273.6  617.58   283.7  618.26
   293.8  619.27     304  620.92   314.1  623.38   324.2  626.34   334.4  629.43
   364.8  639.06
#Mann= 3 , 0 , 0
       0      .1       0   154.6    .045       0   169.6     .08       0
Bank Sta=154.6,169.6
XS Rating Curve= 0 ,0
Exp/Cntr=0.3,0.1

Type RM Length L Ch R = 1 ,6355.4  ,227.5,227.1,226.7
XS GIS Cut Line= 2
     1545947.587      347932.695     1545639.258      348173.824
#Sta/Elev= 30
      10  654.09    20.1  650.56    30.1  647.47    40.1  644.74    50.2  641.31
    80.3  628.49    90.3  624.49   110.4  616.95   120.4  614.36   130.5  613.03
   170.6  611.15   190.7  610.31   210.8  609.63   220.8  609.07   230.8  607.93
   240.9  606.01   243.4  605.72   250.9  604.86   258.4  604.92   260.9  604.94
     271  606.79     281  610.39   311.1  624.06   321.2  628.24   331.2  632.04
   341.2  635.72   351.3  639.23   361.3  642.54   371.3  645.67   391.4  651.65
#Mann= 3 , 0 , 0
       0      .1       0   243.4    .045       0   258.4     .08       0
Bank Sta=243.4,258.4
XS Rating Curve= 0 ,0
Exp/Cntr=0.3,0.1

Type RM Length L Ch R = 1 ,6128.3  ,137.8,136.8,136
XS GIS Cut Line= 2
     1545805.281      347760.742     1545508.811      347999.895
#Sta/Elev= 30
      10  655.93    90.2  634.75   110.3  629.97   120.3  626.92   130.3  623.19
   140.3  619.12   150.4  615.17   160.4  611.59   170.4  608.66   180.4  606.06
   190.5  603.59     193  603.29   200.5  602.38     208  602.57   210.5  602.64
   220.5   604.4   230.5  606.67   250.6  610.64   260.6  613.28   270.6  617.41
   290.7  626.75   300.7  630.68   310.7  633.44   320.8  635.41   330.8  636.77
   340.8   637.8   350.8  638.56   360.9  639.18   370.9  640.13   380.9  641.76
#Mann= 3 , 0 , 0
       0      .1       0     193    .045       0     208     .08       0
Bank Sta=193,208
XS Rating Curve= 0 ,0
Exp/Cntr=0.3,0.1

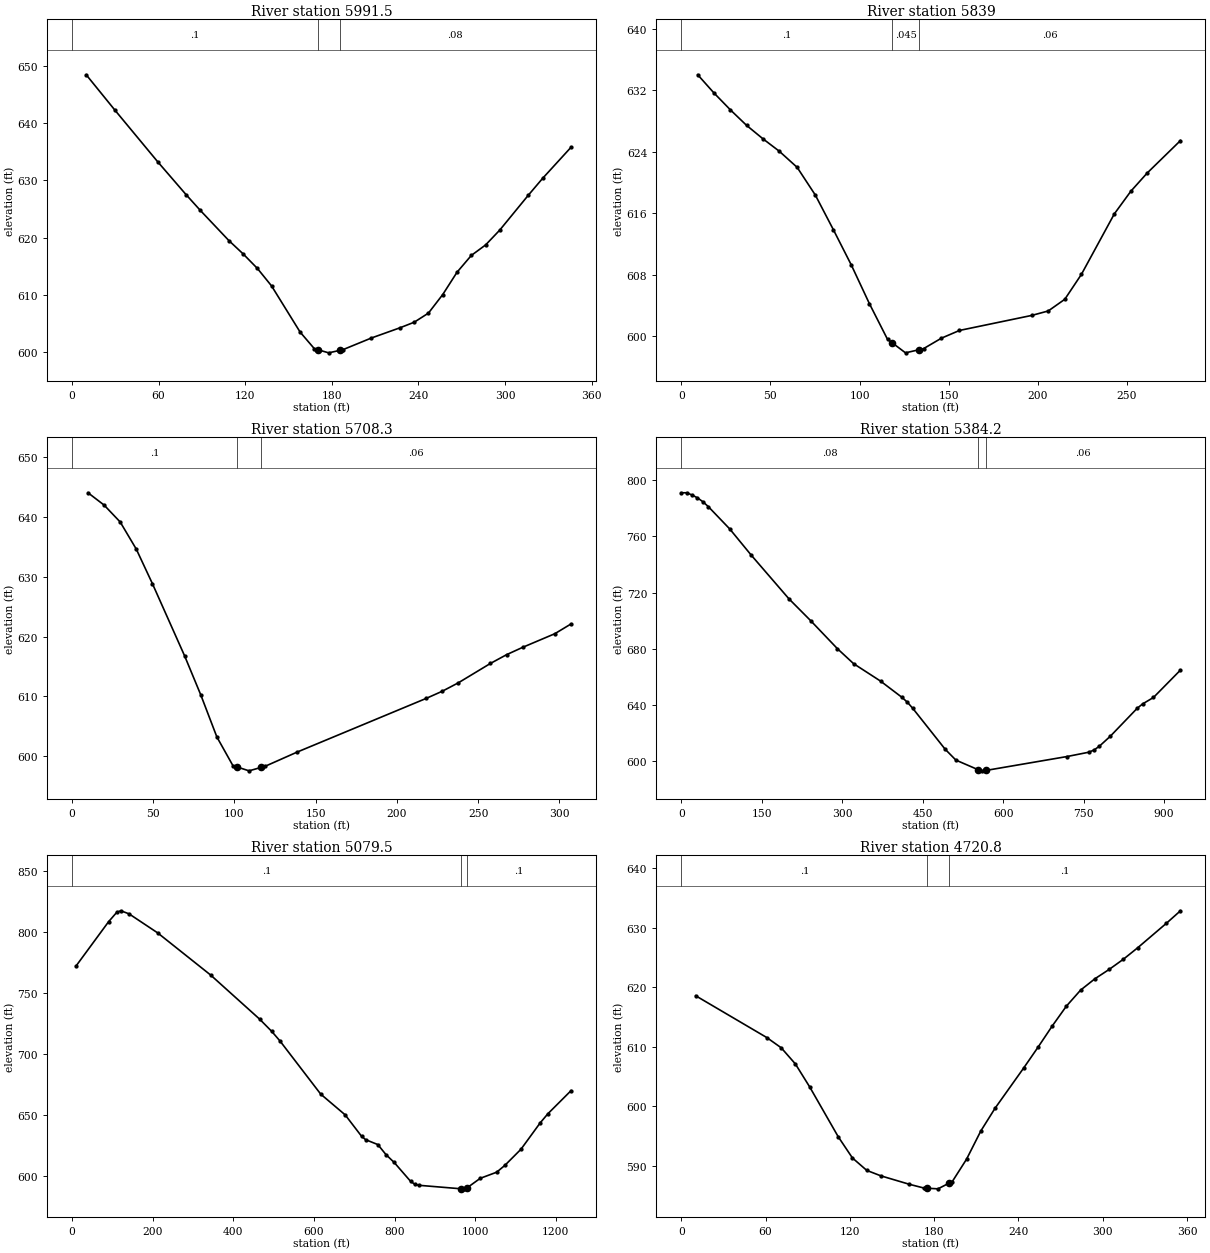
Type RM Length L Ch R = 1 ,5991.5  ,144.4,152.5,160.5
XS GIS Cut Line= 2
     1545705.383      347658.324     1545446.465      347887.594
#Sta/Elev= 27
     9.9   648.5    29.6  642.36    59.3   633.3      79  627.53    88.9  624.76
   108.7  619.47   118.6  617.13   128.5  614.58   138.3  611.52   158.1  603.43
     168  600.51   170.4  600.34   177.9   599.8   185.4  600.22   187.7  600.35
   207.5   602.4   227.3  604.19   237.1  605.16     247  606.76   256.9  610.01
   266.8  613.92   276.7  616.86   286.6   618.7   296.4   621.3   316.2  627.41
   326.1  630.36   345.8  635.81
#Mann= 3 , 0 , 0
       0      .1       0   170.4    .045       0   185.4     .08       0
Bank Sta=170.4,185.4
XS Rating Curve= 0 ,0
Exp/Cntr=0.3,0.1

Type RM Length L Ch R = 1 ,5839    ,132.1,130.7,129.3
XS GIS Cut Line= 4
     1545586.205      347597.162     1545547.378      347635.989
     1545415.125      347686.949     1545352.031       347741.55
#Sta/Elev= 26
     9.2     634    18.3  631.64    27.5  629.45    36.6  627.43    45.8  625.68
    54.9  624.08      65  621.97    75.2  618.37    85.3  613.88    95.4  609.28
   105.5  604.28   115.7  599.63   118.3  599.18   125.8  597.87   133.3  598.27
   135.9  598.41     146  599.78   156.1  600.78   196.6  602.73   205.9  603.31
   215.2  604.83   224.5  608.06     243  615.93   252.3  618.88   261.5  621.25
   280.1  625.45
#Mann= 3 , 0 , 0
       0      .1       0   118.3    .045       0   133.3     .06       0
Bank Sta=118.3,133.3
XS Rating Curve= 0 ,0
Exp/Cntr=0.3,0.1

Type RM Length L Ch R = 1 ,5708.3  ,341.2,324.1,306.9
XS GIS Cut Line= 2
     1545530.552      347495.895     1545251.324      347623.856
#Sta/Elev= 22
     9.9  644.06    19.8     642    29.7  639.17    39.6  634.63    49.5  628.87
    69.4  616.73    79.3  610.23    89.2  603.19    99.1  598.38   101.5  598.18
     109  597.52   116.5   598.1   118.9  598.28   138.7  600.67     218  609.64
   227.9  610.84   237.8  612.25   257.6   615.5   267.5  616.96   277.4  618.19
   297.2  620.47   307.2  622.11
#Mann= 3 , 0 , 0
       0      .1       0   101.5    .045       0   116.5     .06       0
Bank Sta=101.5,116.5
XS Rating Curve= 0 ,0
Exp/Cntr=0.3,0.1

Type RM Length L Ch R = 1 ,5384.2  ,321.8,304.8,287.7
XS GIS Cut Line= 4
     1545772.295      347155.368     1545266.694      347235.323
     1545219.661      347352.905     1545085.227      347612.217
#Sta/Elev= 30
       0  791.17      10  791.17    20.1  789.57    30.1  787.56    40.1  784.81
    50.2  781.34    90.3  765.35   130.5  746.61   200.7  715.51   240.9  700.05
   291.1  679.94   321.2  669.28   371.4  656.86   411.5  645.22   421.6  641.73
   431.6  637.37   491.8   608.3   511.9  600.51   553.1   593.7   560.6  592.85
   568.1  593.15   719.1  603.05   759.4  606.11   769.5  607.71   779.5  610.44
   799.7  617.48     850  637.48   860.1   640.6   880.3  645.18   930.6  664.71
#Mann= 3 , 0 , 0
       0     .08       0   553.1    .045       0   568.1     .06       0
Bank Sta=553.1,568.1
XS Rating Curve= 0 ,0
Exp/Cntr=0.3,0.1

Type RM Length L Ch R = 1 ,5079.5  ,359.2,358.7,358.2
XS GIS Cut Line= 4
     1544951.212      346384.109     1544899.879      347151.166
     1545021.769      347463.581      1545010.53      347596.839
#Sta/Elev= 30
    10.1  772.22      91  808.66   111.3  816.38   121.4   817.6   141.6  815.08
   212.4   799.5   343.9  764.87   465.3  728.69   495.7  718.51   515.9  710.73
     617  667.06   677.7  650.01   718.2   632.5   728.3  629.67   758.7  625.63
   778.9  617.38   799.3  610.93   839.9  595.46   850.1  593.11   860.2  592.21
   964.5  589.34     972  589.29   979.5  590.01  1012.7  597.93  1053.3  602.94
  1073.6  608.52  1113.7  621.82  1161.4  643.49  1180.5  650.97  1237.9  669.93
#Mann= 3 , 0 , 0
       0      .1       0   964.5    .045       0   979.5      .1       0
Bank Sta=964.5,979.5
XS Rating Curve= 0 ,0
Exp/Cntr=0.3,0.1

Type RM Length L Ch R = 1 ,4720.8  ,228.8,227.6,226.3
XS GIS Cut Line= 2
     1544564.058       347274.53     1544700.434      347602.624
#Sta/Elev= 29
    10.2  618.61    60.9  611.57    71.1  609.86    81.2  607.14    91.4  603.27
   111.7   594.9   121.8  591.34     132  589.25   142.1  588.33   162.4  586.91
   172.6  586.29   175.2  586.25   182.7  586.15   190.2  587.06   192.9  587.38
     203  591.12   213.2  595.88   223.3  599.69   243.6  606.43   253.8  609.92
   263.9  613.48   274.1  616.86   284.2  619.55   294.4  621.46   304.6  623.04
   314.7  624.75   324.9  626.68   345.2  630.77   355.3  632.89
#Mann= 3 , 0 , 0
       0      .1       0   175.2    .045       0   190.2      .1       0
Bank Sta=175.2,190.2
XS Rating Curve= 0 ,0
Exp/Cntr=0.3,0.1