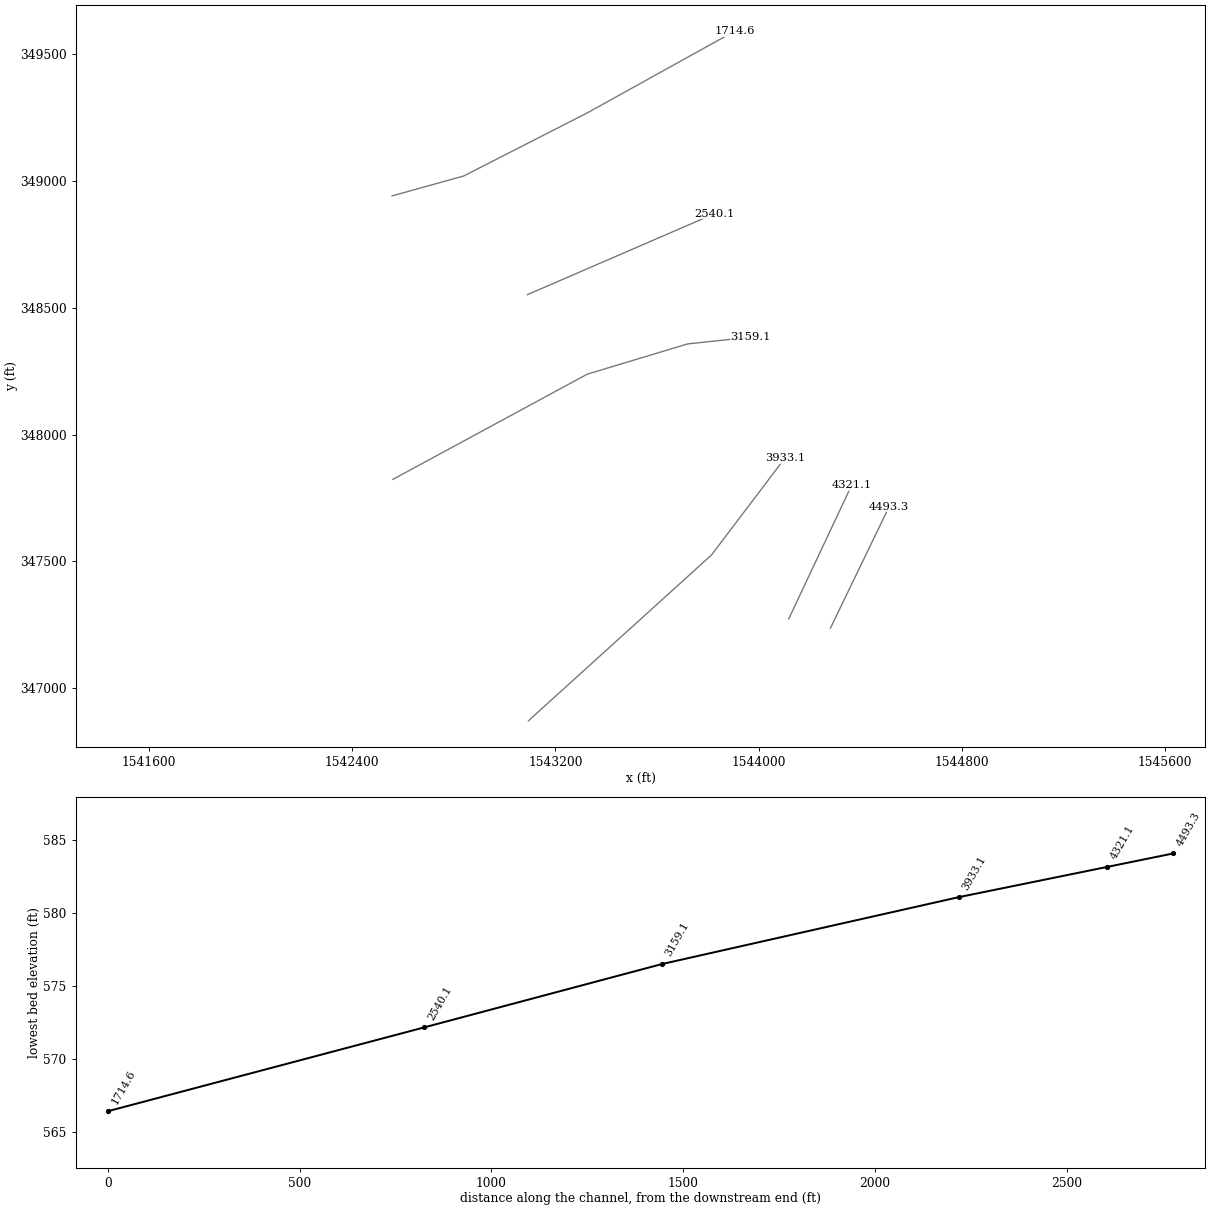
HEC-RAS study SOUTCMPCR.prj: SOUTCMPCR

--- SOUTCMPCR.g01 (geometry) --- (continued)

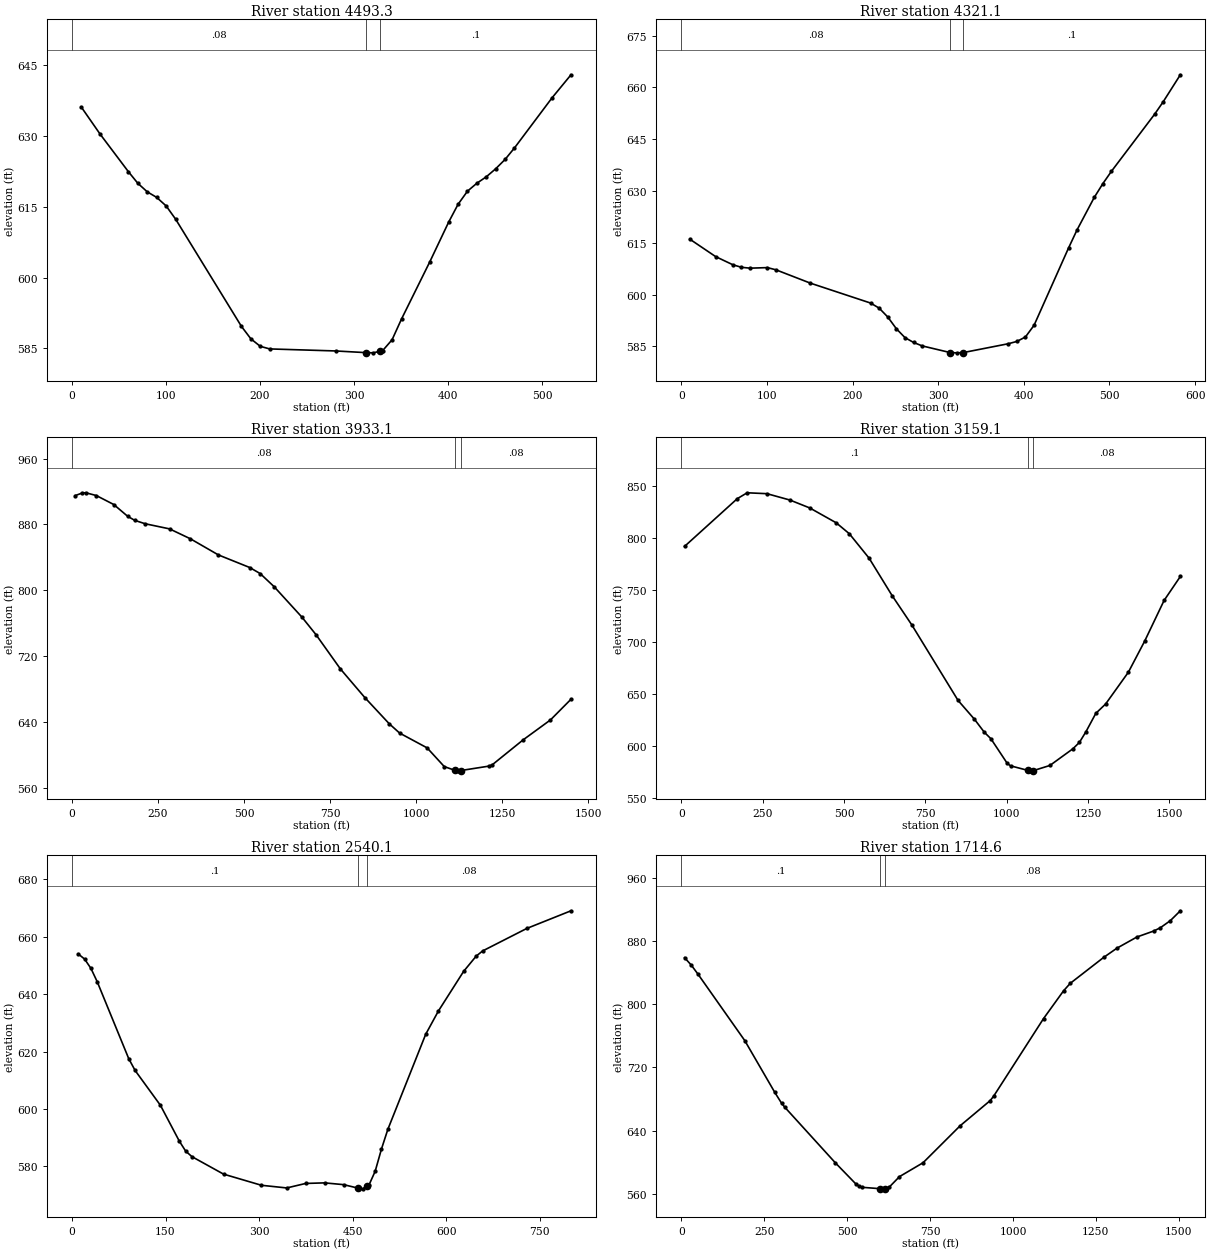
Type RM Length L Ch R = 1 ,4493.3  ,172,172.2,172.3
XS GIS Cut Line= 2
     1544283.013      347237.823        1544514.      347715.777
#Sta/Elev= 30
      10  636.11      30  630.38    60.1  622.42    70.1  619.97    80.1  618.17
    90.1  616.99   100.2  615.18   110.2   612.4   180.3  589.66   190.3  587.03
   200.3  585.44   210.3  584.89   280.4  584.46     313   584.1   320.5  584.06
     328  584.42   330.5  584.54   340.5  586.83   350.6  591.25   380.6  603.33
   400.6  611.72   410.7  615.53   420.7  618.31   430.7  619.99   440.7  621.35
   450.7  623.05   460.7  625.03   470.7  627.47   510.8  638.12   530.8  642.96
#Mann= 3 , 0 , 0
       0     .08       0     313    .045       0     328      .1       0
Bank Sta=313,328
XS Rating Curve= 0 ,0
Exp/Cntr=0.3,0.1

Type RM Length L Ch R = 1 ,4321.1  ,391.8,388,384.1
XS GIS Cut Line= 2
     1544118.559      347273.883     1544366.817      347801.157
#Sta/Elev= 30
      10  616.04    40.2  610.99    60.3  608.63    70.3   607.9    80.4  607.65
   100.5  607.81   110.5  607.18   150.7  603.32   221.1  597.55   231.1  596.08
   241.2   593.5   251.2  590.11   261.3  587.53   271.3  586.15   281.3  585.15
     314  583.22   321.5  583.14     329   583.2   381.8  585.77   391.9  586.44
   401.9  587.73     412  591.12   452.2  613.46   462.2  618.74   482.3  628.14
   492.4  632.15   502.4  635.71   552.7  652.19   562.7  655.78   582.8  663.63
#Mann= 3 , 0 , 0
       0     .08       0     314    .045       0     329      .1       0
Bank Sta=314,329
XS Rating Curve= 0 ,0
Exp/Cntr=0.3,0.1

Type RM Length L Ch R = 1 ,3933.1  ,788.5,773.9,759.4
XS GIS Cut Line= 3
     1543093.631       346872.84     1543814.581      347525.822
      1544103.18      347906.612
#Sta/Elev= 30
    10.1  915.14    30.4  918.27    40.5  918.45    70.9  915.09   121.6  904.21
   162.1  889.87   182.4  885.02   212.8  880.87   283.7  874.65   344.5  862.58
   425.6  843.06   516.7  827.77   547.1  820.43   587.7  804.49   668.7  767.45
   709.3  746.34   780.2  704.76   851.1  670.04     922  638.28   952.4  626.88
  1032.4  608.91  1082.2  586.22  1114.5  581.49    1122  581.07  1129.5   581.4
  1211.6  586.77  1221.6   588.4  1311.1  618.57  1390.8  642.84  1450.5  667.95
#Mann= 3 , 0 , 0
       0     .08       0  1114.5    .045       0  1129.5     .08       0
Bank Sta=1114.5,1129.5
XS Rating Curve= 0 ,0
Exp/Cntr=0.3,0.1

Type RM Length L Ch R = 1 ,3159.1  ,612.7,619,621.8
XS GIS Cut Line= 4
     1542559.559      347823.361     1543325.324      348237.872
     1543720.906      348356.992     1543969.164      348383.355
#Sta/Elev= 30
    10.1     792   172.1  837.83   202.5  843.49   263.3  842.62   334.1  836.49
   394.9  828.91   475.9   814.7   516.4  804.17   577.1  780.72     648  744.69
   708.8  716.42   850.5  644.12     901  625.98   931.2  613.54   951.4  607.34
  1001.7  583.62  1011.8  581.31  1064.8  576.95  1072.3   576.5  1079.8  576.51
  1132.7  581.66  1203.3  597.66  1223.4  603.81  1243.6  614.11  1273.8   631.7
  1303.9  640.67  1373.8  671.19  1423.7  700.91  1483.6  740.12  1533.5  763.11
#Mann= 3 , 0 , 0
       0      .1       0  1064.8    .045       0  1079.8     .08       0
Bank Sta=1064.8,1079.8
XS Rating Curve= 0 ,0
Exp/Cntr=0.3,0.1

Type RM Length L Ch R = 1 ,2540.1  ,822.9,825.6,825.8
XS GIS Cut Line= 2
     1543089.939      348551.121     1543824.164      348868.886
#Sta/Elev= 30
    10.1  654.04    20.3  652.25    30.4  649.02    40.5  644.37    91.1  617.52
   101.3  613.42   141.8  601.31   172.2  588.78   182.3  585.33   192.4  583.39
     243  577.31   303.8  573.42   344.3  572.49   374.7  574.06   405.1  574.26
   435.5  573.64   458.3  572.45   465.8  572.18   473.3   573.1     476  573.44
   486.1  578.31   496.2  586.07   506.4  592.91   567.1  626.05   587.4  634.14
   627.9  647.97   648.1   653.3   658.3  655.08   729.1  662.92     800  669.08
#Mann= 3 , 0 , 0
       0      .1       0   458.3    .045       0   473.3     .08       0
Bank Sta=458.3,473.3
XS Rating Curve= 0 ,0
Exp/Cntr=0.3,0.1

Type RM Length L Ch R = 1 ,1714.6  ,1691.1,1714.6,1739.3
XS GIS Cut Line= 4
     1542556.528       348939.96     1542837.995      349017.981
     1543326.681      349267.563      1543907.17      349589.418
#Sta/Elev= 30
    10.1  858.67    30.2  849.32    50.4   837.9   191.4  753.93     282  688.36
   302.2  674.84   312.4   669.5   464.8  599.23   525.8  572.87     536  569.82
   546.1  568.36   599.6  566.63   607.1  566.45   614.6   566.7   627.4  568.82
   657.9   581.9     729  599.46   840.8  646.21   931.3  677.99   941.4  683.36
  1092.2  781.74  1152.6  816.86  1172.7  826.27  1273.3  859.01  1313.5  870.75
  1373.8  884.89  1424.1  892.39  1444.2  896.52  1474.4  905.52  1504.6  918.02
#Mann= 3 , 0 , 0
       0      .1       0   599.6    .045       0   614.6     .08       0
Bank Sta=599.6,614.6
XS Rating Curve= 0 ,0
Exp/Cntr=0.3,0.1

Chan Stop Cuts=-1
Use User Specified Reach Order=0